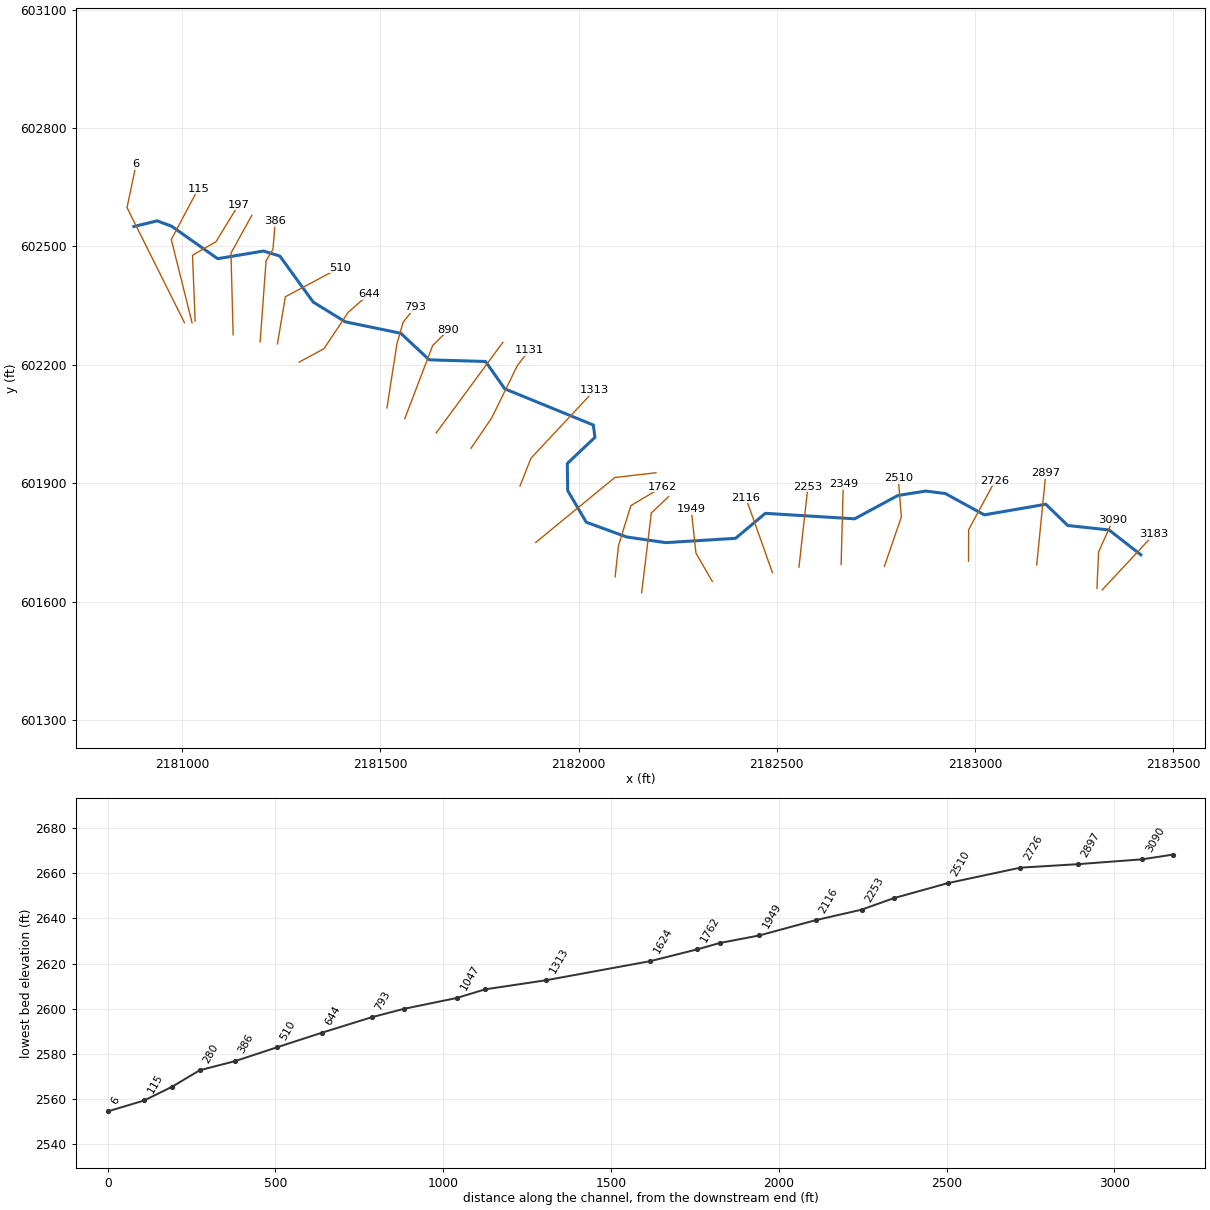
--- FALLRN2.prj (project) ---

Proj Title=FALLRN2
Current Plan=p01
Default Exp/Contr=0,0
English Units
Geom File=g01
Flow File=f01
Plan File=p01
BEGIN DESCRIPTION:
----------MODEL BY WOOD PLC 2022----------
AFH study
Randolph County, WV
HEC-RAS Version: RAS 6.2
Vertical Datum: NAVD88
Projection: NAD 1983 StatePlane West Virginia S FIPS 4702 (US Feet)
Terrain: 1-meter LIDAR (FEMA Region III 3DEP collected 2016-2018)
Land Use: 2019 NLCD
Hydrologic Method:
WV SIR2010-5033 regression equations
Additional Model Notes:
None
END DESCRIPTION:
DSS Export Rating Curves= 0
DSS Export Rating Curve Sorted= 0
DSS Export Volume Flow Curves= 0
DXF OffsetX= 0
DXF OffsetY= 0
DXF ScaleX= 0
DXF ScaleY= 0

--- FALLRN2.p01 (plan) ---

Plan Title=Floodplain
Program Version=6.20
Short Identifier=Floodplain
Geom File=g01
Flow File=f01
Subcritical Flow
K Sum by GR= 0
Std Step Tol= 0.01
Critical Tol= 0.01
Num of Std Step Trials= 20
Max Error Tol= 0.3
Flow Tol Ratio= 0.001
Split Flow NTrial= 30
Split Flow Tol= 0.02
Split Flow Ratio= 0.02
Log Output Level= 0
Friction Slope Method= 1
Unsteady Friction Slope Method= 2
Unsteady Bridges Friction Slope Method= 1
Parabolic Critical Depth
Global Vel Dist= 0 , 0 , 0
Global Log Level= 0
CheckData=True
Encroach Param=-1 ,0,0, 0
Mapping Interval=1HOUR
Computation Time Step Use Courant=        0
Computation Time Step Use Time Series=    0
Computation Time Step Count To Double=0
Computation Time Step Max Doubling=0
Computation Time Step Max Halving=0
Computation Time Step Residence Courant=0
Run HTab= 0
Run UNet= 0
Run Sediment= 0
Run PostProcess= 0
Run WQNet= 0
Run RASMapper=-1
UNET Theta= 0
UNET Theta Warmup= 0
UNET ZTol= 0
UNET ZSATol= 0
UNET MxIter= 0
UNET Max Iter WO Improvement= 0
UNET MaxInSteps= 0
UNET DtIC= 0
UNET DtMin= 0
UNET MaxCRTS= 0
UNET WFStab= 0
UNET SFStab= 0
UNET WFX= 1
UNET SFX= 1
UNET Gravity=32.174
UNET 1D Methodology=Finite Difference
UNET DSS MLevel= 1
UNET Pardiso=0
UNET DZMax Abort= 0
UNET Use Existing IB Tables= 0
UNET Froude Reduction=False
UNET Froude Limit= 0
UNET Froude Power= 0
UNET D1 Cores= 0
UNET WindReference=Eulerian
UNET WindDragFormulation=Hsu (1988)
UNET D2 Coriolis=0
UNET D2 Cores= 0
UNET D2 Theta= 1
UNET D2 Theta Warmup= 1
UNET D2 Z Tol= 0.01
UNET D2 Volume Tol= 0.01
UNET D2 Max Iterations= 20
UNET D2 Equation= 0
UNET D2 RampUpFraction=0.1
UNET D2 TimeSlices= 1
UNET D2 Turbulence Formulation=Non-Conservative (original)
UNET D2 Eddy Viscosity=0.3
UNET D2 Transverse Eddy Viscosity=0.1
UNET D2 Smagorinsky Mixing=0
UNET D2 BCVolumeCheck=0
UNET D2 Cores=0
UNET D2 SolverType=PARDISO (Direct)
UNET D2 Minimum Iterations= 2147483647
UNET D2 Maximum Iterations= 2147483647
UNET D2 Restart Number= 10
UNET D2 Relaxation Coeff=1.3
UNET D2 SOR Precondition Iterations= 10
UNET D2 ILUT Maximum Fill= 8
UNET D2 ILUT Tolerance=1E-08
UNET D1D2 MaxIter= 0
UNET D1D2 ZTol=0.01
UNET D1D2 QTol=0.1
UNET D1D2 MinQTol=1
Write IC File= 0
Write IC File at Fixed DateTime=0
Write IC File at Sim End=0
Echo Input=False
Echo Parameters=False
Echo Output=False
Write Detailed= 0
HDF Write Warmup=0
HDF Write Time Slices=0
HDF Flush=0
HDF Compression= 1
HDF Chunk Size= 1
HDF Spatial Parts= 1
HDF Use Max Rows=0
HDF Fixed Rows= 1
Calibration Method= 0
Calibration Iterations= 20
Calibration Max Change=0.05
Calibration Tolerance=0.2
Calibration Maximum=1.5
Calibration Minimum=0.5
Calibration Optimization Method= 1
WQ AD Non Conservative
WQ ULTIMATE=-1
WQ Max Comp Step=1HOUR
WQ Output Interval=15MIN
WQ Output Selected Increments= 0
WQ Output face flow=0
WQ Output face velocity=0
WQ Output face area=0
WQ Output face dispersion=0
WQ Output cell volume=0
WQ Output cell surface area=0
WQ Output cell continuity=0
WQ Output cumulative cell continuity=0
WQ Output face conc=0
WQ Output face dconc_dx=0
WQ Output face courant=0
WQ Output face peclet=0
WQ Output face adv mass=0
WQ Output face disp mass=0
WQ Output cell mass=0
WQ Output cell source sink temp=0
WQ Output nsm pathways=0
WQ Output nsm derived pathways=0
WQ Create Restart=0
WQ Fixed Restart=0
WQ System Summary=0
WQ Write To DSS=0
Sorting and Armoring Iterations= 10
XS Update Threshold= 0.02
Bed Roughness Predictor= 0
Hydraulics Update Threshold= 0.02
Energy Slope Method= 1
Volume Change Method= 1
Sediment Retention Method= 0
Sediment TS Multiplier= 1
Warm Up Method= 0
XS Weighting Method= 0
Number of US Weighted Cross Sections= 1
Number of DS Weighted Cross Sections= 1
Upstream XS Weight=0
Main XS Weight=1
Downstream XS Weight=0
Number of DS XS's Weighted with US Boundary= 1
Upstream Boundary Weight= 1
Weight of XSs Associated with US Boundary= 0
Number of US XS's Weighted with DS Boundary= 1
Downstream Boundary Weight= 0.5
Weight of XSs Associated with DS Boundary= 0.5
Percentile Method= 0
Sediment Output Level= 3
Mass or Volume Output= 0
Output Increment Type= 1
Profile and TS Output Increment= 1
Transport Output Increment 1
XS Output Flag= 0
XS Output Increment= 10
Read HDF5 Sediment Hotstart= 0
Sediment Hotstart Type= 0
Write Gradation File= 0
Read Gradation Hotstart= 0
Write HDF5 File= 1
Write Binary Output= 1
Write DSS Sediment File= 0
DSS Sediment Output Type= 1
SV Curve= 0
Specific Gage Flag= 0
Subcell Erosion Methods= 0
Subcell Deposition Methods= 0
Advection Scheme= 1
Matrix Solver= 0
Implicit Weighting Factor= 1
Maximum Outer Loop Convergence Iterations= 5
Convergence Maximum Absolute= 0.001
Convergence RMSE= 0.0001
Grain Fractions Max Abs Error= 0.001
Max Subgrid Regions= 1
Max Subgrid Length Scale= 3.402823E+38
Initial Layer Thickness= 3.402823E+38
Min Layer Thickness= 3.402823E+38
Max Layer Thickness= 3.402823E+38
Number of Layers= 5

--- FALLRN2.f01 (steady flow) ---

Flow Title=Flow
Program Version=6.20
Number of Profiles= 1
Profile Names=P100yr
River Rch & RM=FALLRN2,Main,3183
     471
Boundary for River Rch & Prof#=FALLRN2,Main            , 1
Up Type= 0
Dn Type= 3
Dn Slope=0.04511
DSS Import GetInterval= 0
DSS Import GetPeak= 0
DSS Import FillOption= 0

--- FALLRN2.g01 (geometry) ---

Geom Title=Geometry
Program Version=6.20

River Reach=FALLRN2         ,Main
Reach XY= 30
      2183418.72      601718.974     2183338.425      601781.908
     2183234.258      601793.193     2183178.852      601847.015
     2183023.755      601820.1032182925.40460841601874.129513274
     2182875.751      601880.432     2182805.438      601869.147
     2182696.498       601810.122182471.16816495601824.013282018
2182396.18216615601760.746733836     2182219.935       601749.79
     2182121.411      601764.113     2182019.414      601801.439
     2181972.539      601881.561     2181971.498      601950.311
     2182041.289      602016.456     2182037.123      602047.706
     2181813.685      602139.373     2181765.248      602208.644
      2181623.06      602212.811     2181551.287      602280.096
     2181411.081      602309.165     2181330.352      602359.165
2181246.22384629602475.679221307     2181204.894      602488.404
     2181089.206      602469.0612180972.69738187 602551.57161399
2180936.46012321602564.7875553832180877.82539984602550.467975899

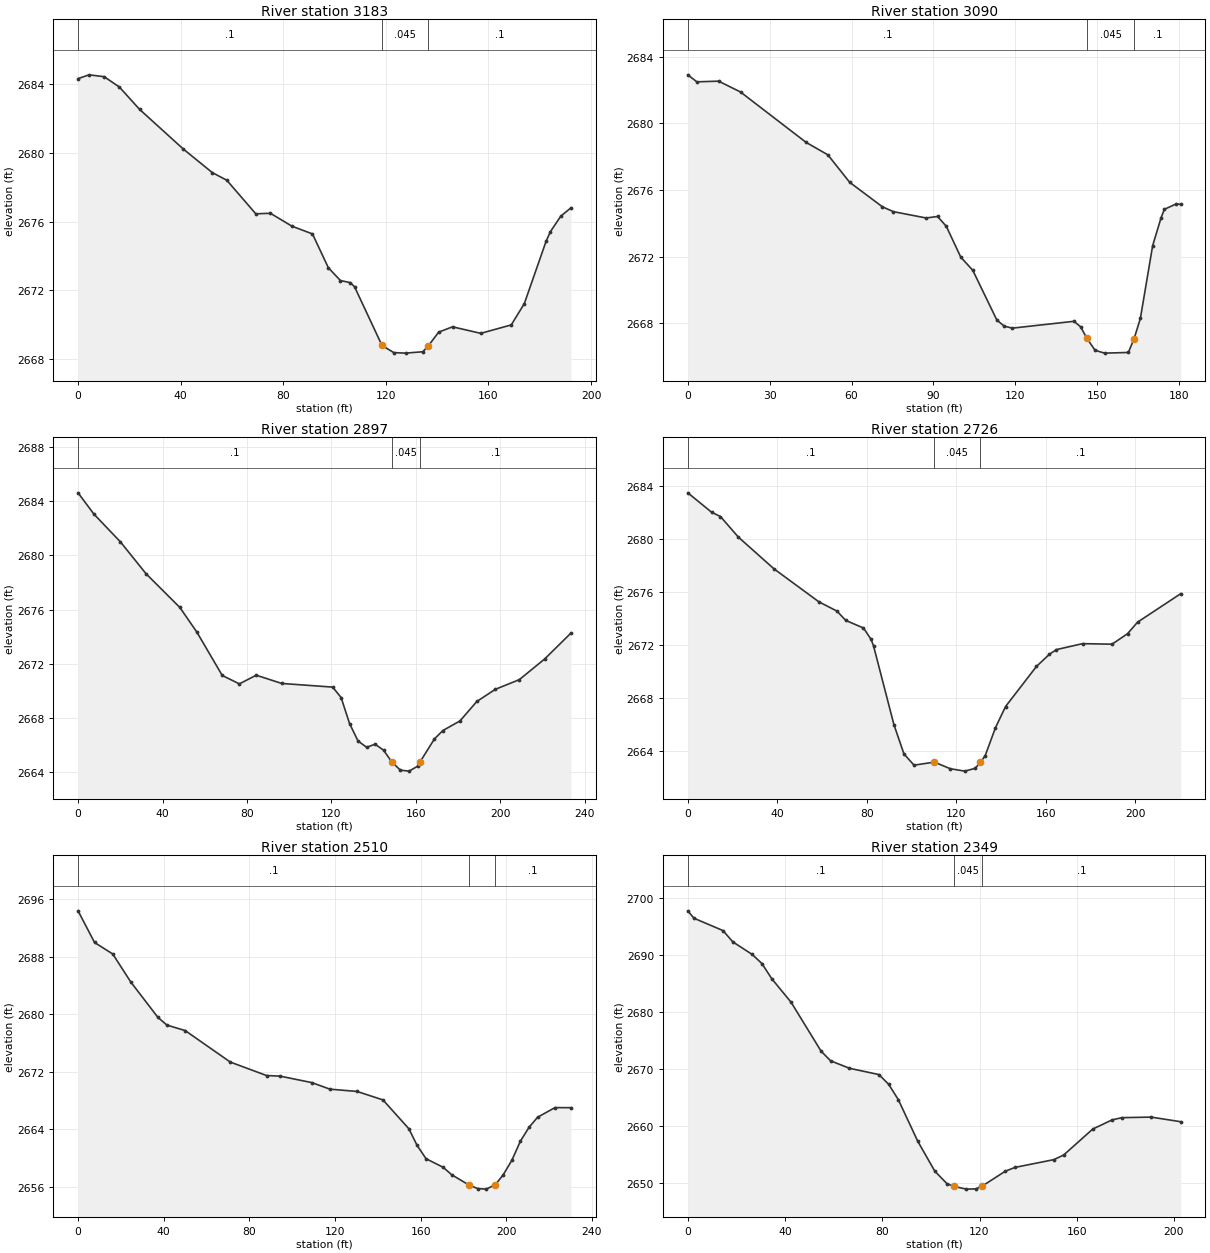
Type RM Length L Ch R = 1 ,3183    ,93,93,93
XS GIS Cut Line= 2
2183321.24162137601630.202558837 2183452.0578205601771.004479353
#Sta/Elev= 30
       0 2684.31     4.3 2684.53    10.2 2684.42    16.1 2683.82      24 2682.52
      41 2680.22    52.3 2678.85      58  2678.4    69.3 2676.45      75 2676.48
    83.4 2675.73    91.4 2675.28    97.6 2673.31   102.3 2672.57   106.1 2672.45
   107.8 2672.21118.49972668.797   123.1 2668.38   127.7 2668.35   134.4 2668.43
136.54972668.769   140.6 2669.57     146 2669.88     157  2669.5   168.9 2669.99
     174 2671.23   182.5 2674.86   184.2 2675.42   188.2 2676.31   192.2  2676.8
#Mann= 3 ,-1,0
       0      .1       0118.4997    .045       0136.5497      .1       0
Bank Sta=118.4997,136.5497
XS Rating Curve= 0 ,0
Exp/Cntr(USF)=0,0
Exp/Cntr=0.3,0.1

Type RM Length L Ch R = 1 ,3090    ,192.5,192.5,192.5
XS GIS Cut Line= 3
2183307.98615108601633.9267681972183312.06119542601726.374806094
2183348.28209182601806.691726189
#Sta/Elev= 30
       0 2682.92     3.3  2682.5    11.3 2682.54    19.3 2681.89    43.3 2678.87
    51.3 2678.12    59.3 2676.47    71.3    2675    75.3 2674.71    87.3 2674.33
    91.5 2674.42    94.7 2673.83     100 2671.98   104.4 2671.19   113.2 2668.21
   115.9 2667.84   118.9 2667.72   141.5 2668.13   143.9  2667.8   146.2 2667.11
   149.2 2666.39   152.7 2666.22   161.4 2666.26  163.51 2667.09   165.8  2668.3
   170.3 2672.67   173.4 2674.35   174.6 2674.85     179 2675.18   180.6 2675.14
#Mann= 3 ,-1,0
       0      .1       0   146.2    .045       0  163.51      .1       0
Bank Sta=146.2,163.51
XS Rating Curve= 0 ,0
Exp/Cntr(USF)=0,0
Exp/Cntr=0.3,0.1

Type RM Length L Ch R = 1 ,2897    ,170.7,170.7,170.7
XS GIS Cut Line= 2
2183155.94488064601693.1848950592183178.95908051601925.518722332
#Sta/Elev= 30
       0 2684.63     7.5 2683.06    20.1    2681    32.2 2678.65    48.2 2676.16
    56.3 2674.33    68.3 2671.13    76.4 2670.51    84.4 2671.15    96.5 2670.54
   120.6 2670.27   124.6  2669.5   128.6 2667.58   132.6 2666.29   136.7 2665.82
   140.7 2666.05   144.7 2665.61   148.7 2664.72   152.7 2664.13   156.8 2664.06
   160.8 2664.42  162.012664.744   168.8 2666.44   172.8 2667.06   180.9 2667.77
   188.9 2669.21   197.7 2670.11     209 2670.82   221.1 2672.36   233.5 2674.27
#Mann= 3 ,-1,0
       0      .1       0   148.7    .045       0  162.01      .1       0
Bank Sta=148.7,162.01
XS Rating Curve= 0 ,0
Exp/Cntr(USF)=0,0
Exp/Cntr=0.3,0.1

Type RM Length L Ch R = 1 ,2726    ,216.6,216.6,216.6
XS GIS Cut Line= 3
2182983.86109248601702.5627640092182984.28187743601782.550271631
2183050.69367464601906.146103146
#Sta/Elev= 30
       0  2683.5    10.6 2682.04    14.6 2681.71    22.6 2680.16    38.5 2677.77
    58.6 2675.28    66.6 2674.59    70.6 2673.88    78.5 2673.31    81.9 2672.45
      83 2671.96    92.1 2666.03    96.6 2663.81   101.1 2662.97   110.2  2663.2
   117.3  2662.7   123.8 2662.52   128.4 2662.73  130.77 2663.18   132.9 2663.69
   137.5  2665.8     142 2667.39   155.8 2670.41   161.6 2671.33   164.7 2671.68
   176.4 2672.13   189.6 2672.09   196.5 2672.88     201 2673.75   220.3  2675.9
#Mann= 3 ,-1,0
       0      .1       0   110.2    .045       0  130.77      .1       0
Bank Sta=110.2,130.77
XS Rating Curve= 0 ,0
Exp/Cntr(USF)=0,0
Exp/Cntr=0.3,0.1

Type RM Length L Ch R = 1 ,2510    ,161.1,161.1,161.1
XS GIS Cut Line= 3
2182771.64427326 601689.897152222182814.38493017601814.831380093
2182806.71353021601912.733055737
#Sta/Elev= 30
       0  2694.4     7.7 2689.99    16.2 2688.39    24.6  2684.5    37.3 2679.56
    41.5 2678.49      50 2677.73    71.1 2673.34      88 2671.47    94.4 2671.38
   109.2 2670.48   117.6 2669.57   130.3 2669.25   142.4 2668.07   154.5 2664.05
   158.3 2661.75   162.5 2659.89   170.5 2658.69   174.5 2657.65   182.5 2656.23
   186.6 2655.73   190.6 2655.65  194.862656.263   198.6 2657.67   202.6 2659.68
   206.6 2662.35   210.6 2664.26   214.6 2665.66   222.7    2667   230.2 2666.99
#Mann= 3 ,-1,0
       0      .1       0   182.5    .045       0  194.86      .1       0
Bank Sta=182.5,194.86
XS Rating Curve= 0 ,0
Exp/Cntr(USF)=0,0
Exp/Cntr=0.3,0.1

Type RM Length L Ch R = 1 ,2349    ,95.7,95.7,95.7
XS GIS Cut Line= 2
2182662.41815006601694.6461140982182667.89772146601897.390255823
#Sta/Elev= 30
       0 2697.67     2.5 2696.38    14.5 2694.21    18.5 2692.24    26.5 2690.04
    30.5 2688.44    34.5 2685.81    42.5 2681.67    54.8 2673.14    58.7 2671.44
    66.5 2670.13    78.6 2669.03    82.6 2667.34    86.6 2664.64    94.6 2657.36
   101.6 2652.14   106.6 2649.95   109.4 2649.48   114.6 2648.99   118.6 2649.04
   121.1 2649.52   130.6 2652.12   134.6 2652.79   150.6 2654.15   154.6 2654.95
   166.6  2659.5   174.6 2661.11   178.6 2661.49   190.6 2661.59   202.8 2660.78
#Mann= 3 ,-1,0
       0      .1       0   109.4    .045       0   121.1      .1       0
Bank Sta=109.4,121.1
XS Rating Curve= 0 ,0
Exp/Cntr(USF)=0,0
Exp/Cntr=0.3,0.1

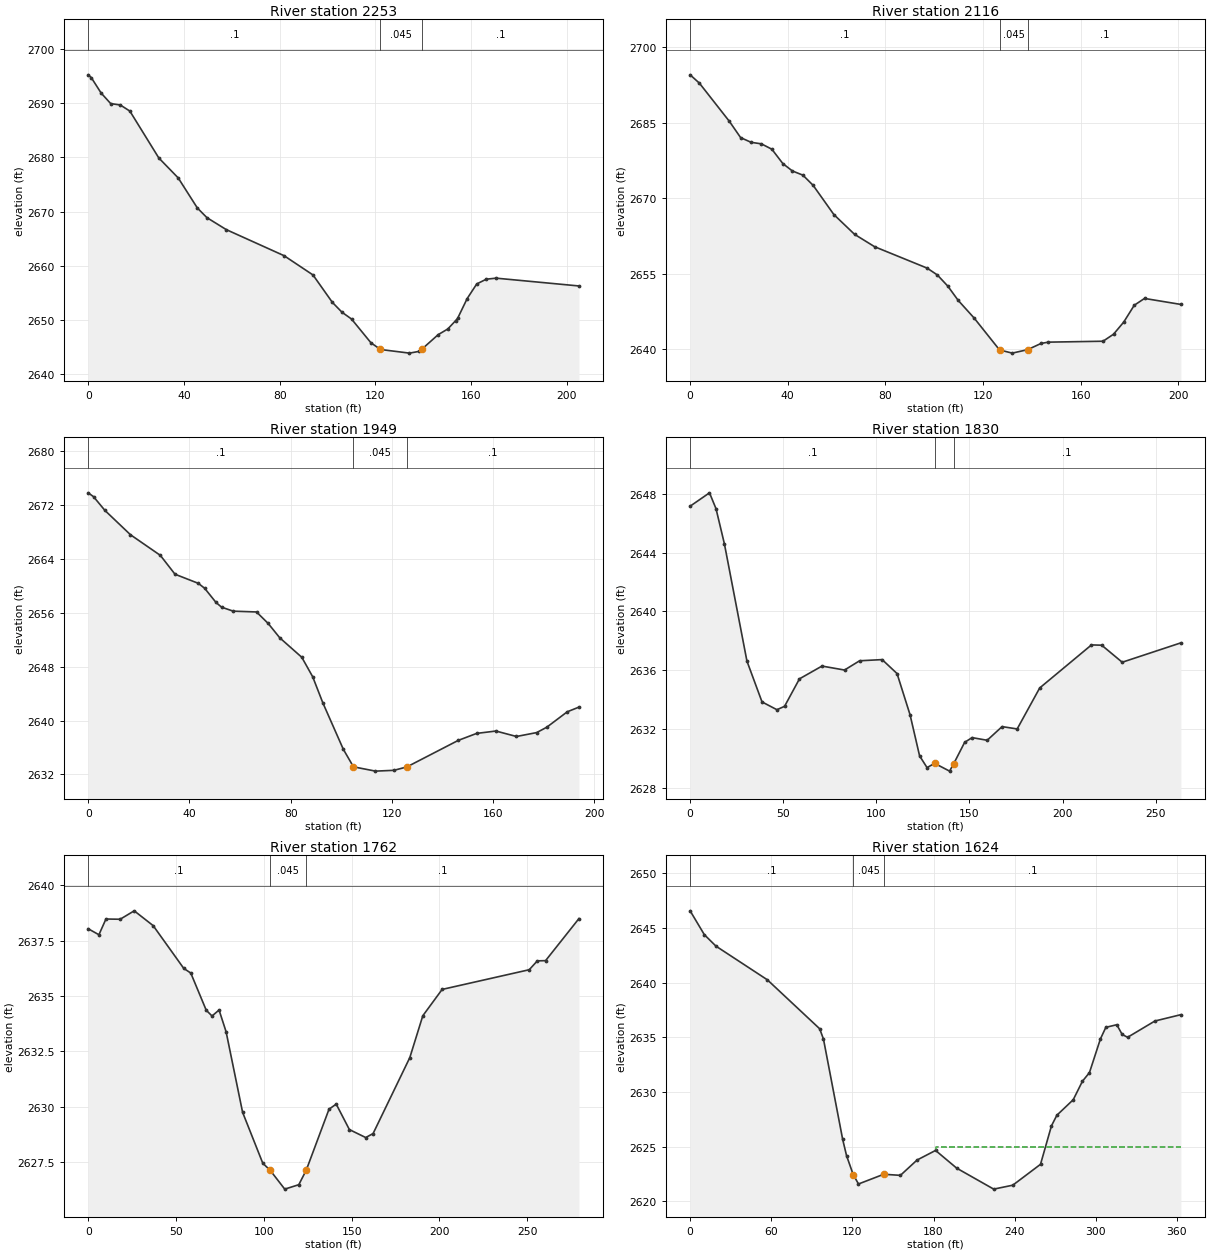
Type RM Length L Ch R = 1 ,2253    ,136.9,136.9,136.9
XS GIS Cut Line= 2
2182556.05242494601687.8458958272182578.64742151601891.627185699
#Sta/Elev= 30
       0 2695.24     1.3 2694.72     5.4 2691.88     9.4 2689.93    13.4 2689.68
    17.4 2688.55    29.5  2679.9    37.6 2676.22    45.6 2670.67    49.6 2668.89
    57.7 2666.68    81.8 2661.88    93.9 2658.32     102 2653.26     106 2651.45
     110 2650.19   118.1 2645.81   122.1 2644.57   134.2  2643.9   138.2 2644.22
  139.26 2644.58   146.2 2647.31   150.2 2648.35   153.5  2649.9   154.3  2650.3
   158.3 2653.96   162.3 2656.66   166.3 2657.54   170.4 2657.73     205 2656.29
#Mann= 3 ,-1,0
       0      .1       0   122.1    .045       0  139.26      .1       0
Bank Sta=122.1,139.26
XS Rating Curve= 0 ,0
Exp/Cntr(USF)=0,0
Exp/Cntr=0.3,0.1

Type RM Length L Ch R = 1 ,2116    ,167.3,167.3,167.3
XS GIS Cut Line= 2
2182489.15410246601673.6410904062182422.08414855601863.197730299
#Sta/Elev= 30
       0 2694.46     3.8 2692.81    16.1 2685.22    20.7    2682      25 2681.07
    29.2 2680.77    33.5  2679.7      38 2676.85    41.9 2675.39    46.2 2674.56
    50.4 2672.54    58.9 2666.74    67.4 2662.81    75.6 2660.36    97.1 2656.12
   101.3 2654.76   105.6 2652.54   109.8 2649.74   116.4  2646.2   126.8 2639.88
     132 2639.25   138.3 2639.94   143.8 2641.17   146.8 2641.43   169.2 2641.61
   173.5    2643   177.7 2645.42     182 2648.75   186.2  2650.1   201.1 2648.91
#Mann= 3 ,-1,0
       0      .1       0   126.8    .045       0   138.3      .1       0
Bank Sta=126.8,138.3
XS Rating Curve= 0 ,0
Exp/Cntr(USF)=0,0
Exp/Cntr=0.3,0.1

Type RM Length L Ch R = 1 ,1949    ,118.4,118.4,118.4
XS GIS Cut Line= 3
2182337.31662075601651.4855222532182296.11474264601723.310417882
2182284.22805258601833.764561388
#Sta/Elev= 30
       0  2673.8     2.1 2673.23     6.6 2671.19    16.7 2667.58    28.5 2664.52
    34.3 2661.72    43.5 2660.37      46 2659.64    50.5 2657.53    52.7 2656.83
    57.3 2656.24    66.5 2656.12    71.1 2654.42    75.7 2652.28    84.4 2649.39
    88.7  2646.5    92.7 2642.64   100.8 2635.74   104.8 2633.14   113.5  2632.5
   120.8 2632.62  125.912633.125   146.2 2637.06   153.5  2638.1   161.1 2638.45
   169.2 2637.64   177.2 2638.22   181.2 2639.02   189.3 2641.31   193.9    2642
#Mann= 3 ,-1,0
       0      .1       0   104.8    .045       0  125.91      .1       0
Bank Sta=104.8,125.91
XS Rating Curve= 0 ,0
Exp/Cntr(USF)=0,0
Exp/Cntr=0.3,0.1

Type RM Length L Ch R = 1 ,1830    ,68.2,68.2,68.2
XS GIS Cut Line= 3
2182159.05612551601622.8705656812182183.55453952601824.982481289
2182226.98354618601866.184359402
#Sta/Elev= 30
       0 2647.16    10.4 2648.07    13.9 2646.99    18.4  2644.6    30.5 2636.62
    38.6 2633.84    46.6 2633.31    50.7 2633.54    58.7 2635.41    70.8 2636.28
    82.9 2636.01      91 2636.64   103.1 2636.72   111.1 2635.77   118.1 2632.96
   123.2 2630.17   127.2 2629.37   131.3 2629.66   139.3 2629.13  141.422629.608
   147.4 2631.09   151.4 2631.41   159.5 2631.23   167.5 2632.16   175.6    2632
   187.7 2634.79   215.5 2637.72     221  2637.7     232 2636.54   263.5 2637.86
#Mann= 3 ,-1,0
       0      .1       0   131.3    .045       0  141.42      .1       0
Bank Sta=131.3,141.42
XS Rating Curve= 0 ,0
Exp/Cntr(USF)=0,0
Exp/Cntr=0.3,0.1

Type RM Length L Ch R = 1 ,1762    ,138.2,138.2,138.2
XS GIS Cut Line= 4
 2182092.2155141  601663.1192958 2182100.7419279601742.414944161
2182131.86333828601843.4529477172182212.43794871601891.627185699
#Sta/Elev= 30
       0 2638.04     6.1 2637.77    10.1 2638.48    18.2 2638.47    26.2 2638.85
      37 2638.18    54.4 2636.25    58.4 2636.04    67.2 2634.36    70.5  2634.1
    74.5 2634.37    78.5 2633.39    87.9 2629.75    99.4 2627.45   103.6 2627.13
   111.9 2626.28   119.9 2626.48  124.16 2627.14   137.1 2629.89   141.2 2630.12
   148.7 2628.97     158 2628.61   162.2 2628.79   183.1 2632.22   190.5 2634.11
   201.5  2635.3   251.1 2636.19   255.7 2636.59   260.4  2636.6   279.4  2638.5
#Mann= 3 ,-1,0
       0      .1       0   103.6    .045       0  124.16      .1       0
Bank Sta=103.6,124.16
XS Rating Curve= 0 ,0
Exp/Cntr(USF)=0,0
Exp/Cntr=0.3,0.1

Type RM Length L Ch R = 1 ,1624    ,311.3,311.3,311.3
XS GIS Cut Line= 3
2181892.08036014601750.430330993 2182091.5197215601914.792417736
2182195.24823356601926.818911888
#Sta/Elev= 30
       0 2646.58    10.5  2644.4    19.1 2643.35    57.1 2640.27    95.8 2635.79
    98.6 2634.85   112.8 2625.67   115.7 2624.17  120.582622.457   124.5 2621.59
  143.17 2622.48   155.5 2622.38   167.8 2623.78   181.5 2624.66   197.1 2623.04
   224.5 2621.12   238.6 2621.48   259.1 2623.39   267.2 2626.91   271.2 2627.88
   283.3  2629.3   290.1 2630.99   295.3 2631.78   303.4 2634.86   307.4 2635.92
   315.5 2636.16   319.5 2635.27   323.5 2635.01   343.7  2636.5   362.9 2637.08
#Mann= 3 ,-1,0
       0      .1       0  120.58    .045       0  143.17      .1       0
#XS Ineff= 2 , 0
                          181.54            2625
Permanent Ineff=
       F       F
Bank Sta=120.58,143.17
XS Rating Curve= 0 ,0
Exp/Cntr(USF)=0,0
Exp/Cntr=0.3,0.1

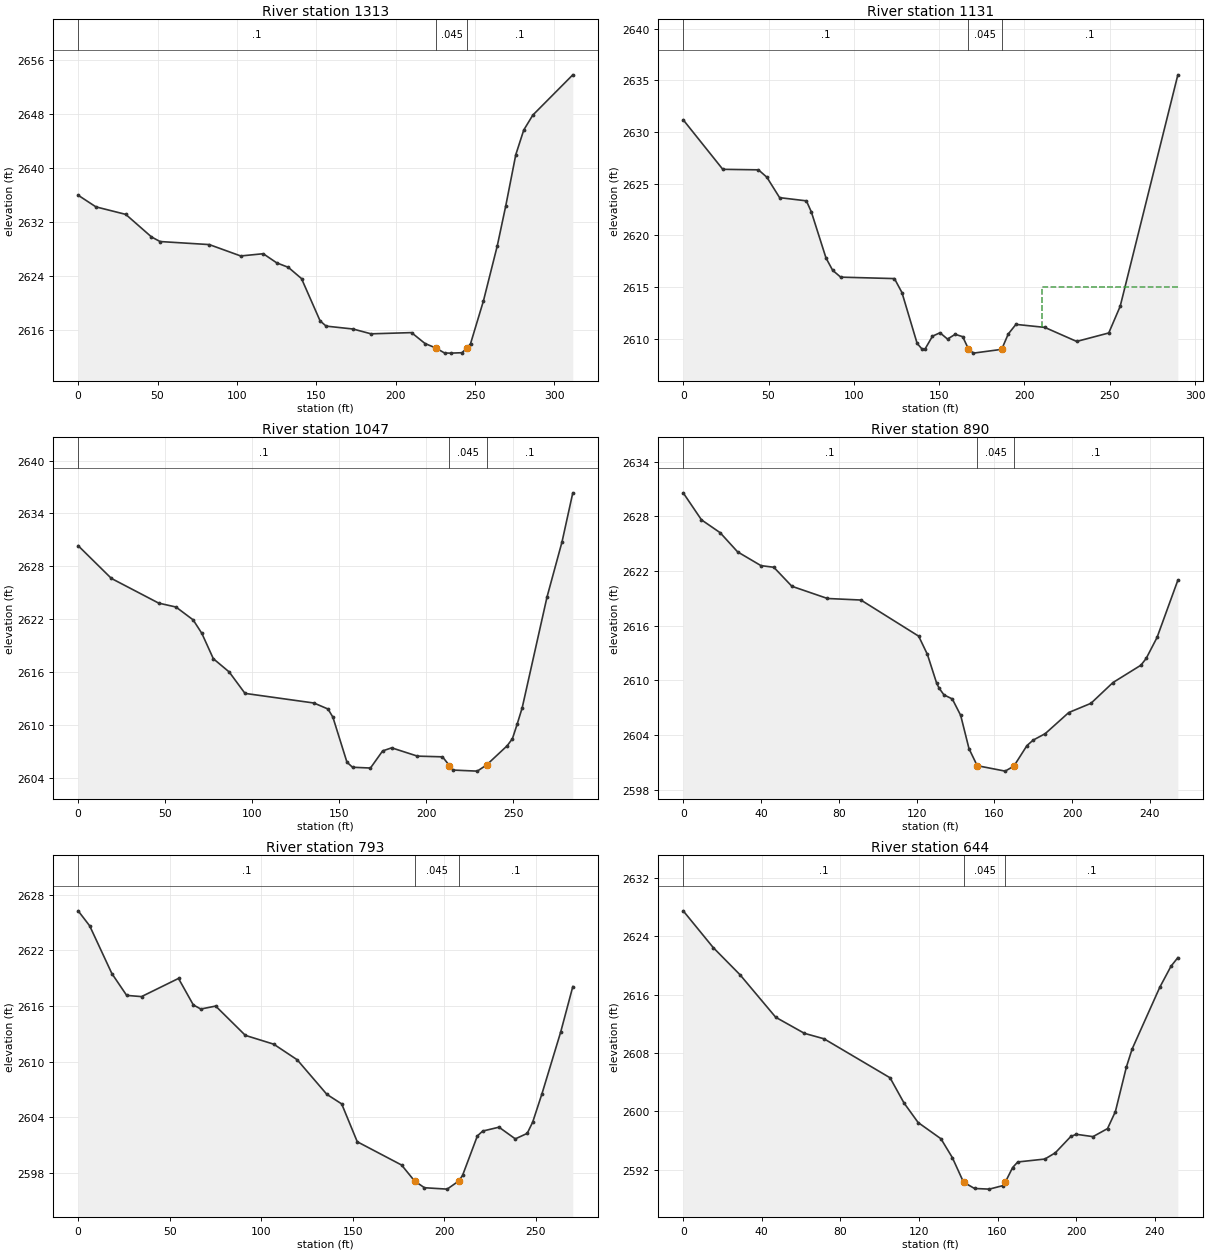
Type RM Length L Ch R = 1 ,1313    ,181.6,181.6,181.6
XS GIS Cut Line= 3
2181852.06301838601893.2531055032181880.06971663601963.878692409
2182040.64625515602136.332208387
#Sta/Elev= 30
       0 2635.96    11.2 2634.24      30 2633.13    46.2  2629.8    51.6 2629.12
    82.6 2628.67   102.4 2626.99   116.6 2627.32   125.1 2625.97   132.4 2625.31
   140.7 2623.65   152.4 2617.41   156.2 2616.63   173.2  2616.2   184.5 2615.49
     210 2615.67   218.5 2614.06   225.3  2613.4   230.8 2612.66   234.6 2612.64
   241.7  2612.7  245.062613.408   247.2 2614.05   255.3 2620.35     264 2628.46
   269.4 2634.43   275.7 2641.96   280.7 2645.59   286.4 2647.79   311.6 2653.74
#Mann= 3 ,-1,0
       0      .1       0   225.3    .045       0  245.06      .1       0
Bank Sta=225.3,245.06
XS Rating Curve= 0 ,0
Exp/Cntr(USF)=0,0
Exp/Cntr=0.3,0.1

Type RM Length L Ch R = 1 ,1131    ,83.8,83.8,83.8
XS GIS Cut Line= 4
2181728.43043917601988.6540175882181781.32474215 602066.60351672
2181845.35468787602198.0041009722181875.45401992602237.318122504
#Sta/Elev= 30
       0 2631.17    23.2 2626.38    44.1 2626.33      49 2625.62    56.5 2623.64
    72.2 2623.33    75.1 2622.26    83.7  2617.8    87.6 2616.61    92.3 2615.95
   123.8 2615.81   128.2 2614.46   137.1 2609.54   140.1 2608.97   141.6 2608.96
   146.1 2610.24   150.5 2610.57   154.9 2609.96   159.4 2610.42   163.8 2610.19
   167.1 2609.03   170.1  2608.6  186.642608.966   190.5 2610.45     195 2611.38
   211.9 2611.09   230.6 2609.73   249.4 2610.55   256.1 2613.13   289.9 2635.52
#Mann= 3 ,-1,0
       0      .1       0   167.1    .045       0  186.64      .1       0
#XS Ineff= 1 ,-1
     210 289.886    2615
Permanent Ineff=
       T
Bank Sta=167.1,186.64
XS Rating Curve= 0 ,0
Exp/Cntr(USF)=0,0
Exp/Cntr=0.3,0.1

Type RM Length L Ch R = 1 ,1047    ,156.6,156.6,156.6
XS GIS Cut Line= 2
2181640.85844488 602027.857462122181808.89863441602257.187672479
#Sta/Elev= 30
       0 2630.35    19.1 2626.64    46.3 2623.84    56.2  2623.4    66.1 2621.94
    71.1 2620.41    77.7 2617.54    86.8 2616.04    95.9 2613.61   135.5 2612.52
   143.6 2611.84   146.4 2610.92   154.5 2605.81   157.7 2605.24     168 2605.15
     175 2607.09   180.2 2607.44     195  2606.5   209.4 2606.42   213.4 2605.43
   215.4 2604.92   229.4  2604.8   234.7 2605.49   246.6 2607.68   249.6 2608.48
   252.3 2610.11   255.2 2611.97   269.5 2624.55   278.1 2630.78   284.3 2636.34
#Mann= 3 ,-1,0
       0      .1       0   213.4    .045       0   234.7      .1       0
Bank Sta=213.4,234.7
XS Rating Curve= 0 ,0
Exp/Cntr(USF)=0,0
Exp/Cntr=0.3,0.1

Type RM Length L Ch R = 1 ,890     ,97.6,97.6,97.6
XS GIS Cut Line= 3
2181561.44119008602063.7669200152181631.79888683602249.195616121
2181671.58057518602288.648530187
#Sta/Elev= 30
       0  2630.6     9.4 2627.63      19 2626.22      28 2624.11      40  2622.6
    46.6 2622.42    55.9 2620.33    74.2 2618.99    91.4 2618.82   121.1 2614.85
   125.6 2612.84   130.4 2609.65   131.7 2609.11   134.1  2608.4   138.4 2607.95
   142.7 2606.15     147 2602.48   151.2 2600.62   165.6 2600.02   170.1 2600.58
   176.8 2602.83     180 2603.43   186.2 2604.14   198.3 2606.46   209.7 2607.47
     221 2609.75   235.4 2611.66   238.1  2612.4   243.7 2614.71   254.4    2621
#Mann= 3 ,-1,0
       0      .1       0   151.2    .045       0   170.1      .1       0
Bank Sta=151.2,170.1
XS Rating Curve= 0 ,0
Exp/Cntr(USF)=0,0
Exp/Cntr=0.3,0.1

Type RM Length L Ch R = 1 ,793     ,149,149,149
XS GIS Cut Line= 4
2181516.46465057602091.0000501672181541.40918248602252.294489532
2181557.11717882602307.8211957892181587.68747819602346.377817967
#Sta/Elev= 30
       0 2626.26     6.3 2624.64    18.4  2619.5    26.5 2617.14    34.6 2617.01
    54.8 2618.97    62.9 2616.11      67 2615.67    75.1 2615.99    91.3 2612.83
   106.8 2611.88   119.6  2610.2   135.8 2606.47   143.9 2605.44   152.4 2601.36
   176.6 2598.85   183.7 2597.13   189.1  2596.4   201.5 2596.25  207.72 2597.11
   209.9 2597.73     218 2601.99   220.9 2602.51   229.8 2602.93   238.7 2601.67
   245.2 2602.26   248.2 2603.48   253.3 2606.56   263.5  2613.2   270.1 2618.09
#Mann= 3 ,-1,0
       0      .1       0   183.7    .045       0  207.72      .1       0
Bank Sta=183.7,207.72
XS Rating Curve= 0 ,0
Exp/Cntr(USF)=0,0
Exp/Cntr=0.3,0.1

Type RM Length L Ch R = 1 ,644     ,134,134,134
XS GIS Cut Line= 4
2181294.74166096602206.9920019982181357.42976173  602240.8165168
 2181418.7648819602333.2701905922181471.08013146602379.271530723
#Sta/Elev= 30
       0 2627.48    15.3 2622.44    28.9 2618.73    47.1  2612.9    61.7  2610.7
    71.7 2609.95   105.3 2604.61   112.4 2601.16   119.6 2598.48   131.2 2596.26
     137 2593.68   142.7 2590.31   148.3 2589.45   155.8 2589.36   162.6 2589.83
  164.042590.356   167.7 2592.32   170.3 2593.08   184.1 2593.48   189.4 2594.33
   197.3 2596.57   200.1 2596.87   208.6 2596.55     216 2597.65     220 2599.98
   225.6 2606.09   228.5 2608.54   242.6 2617.01   248.3 2619.89   251.8 2621.07
#Mann= 3 ,-1,0
       0      .1       0   142.7    .045       0  164.04      .1       0
Bank Sta=142.7,164.04
XS Rating Curve= 0 ,0
Exp/Cntr(USF)=0,0
Exp/Cntr=0.3,0.1

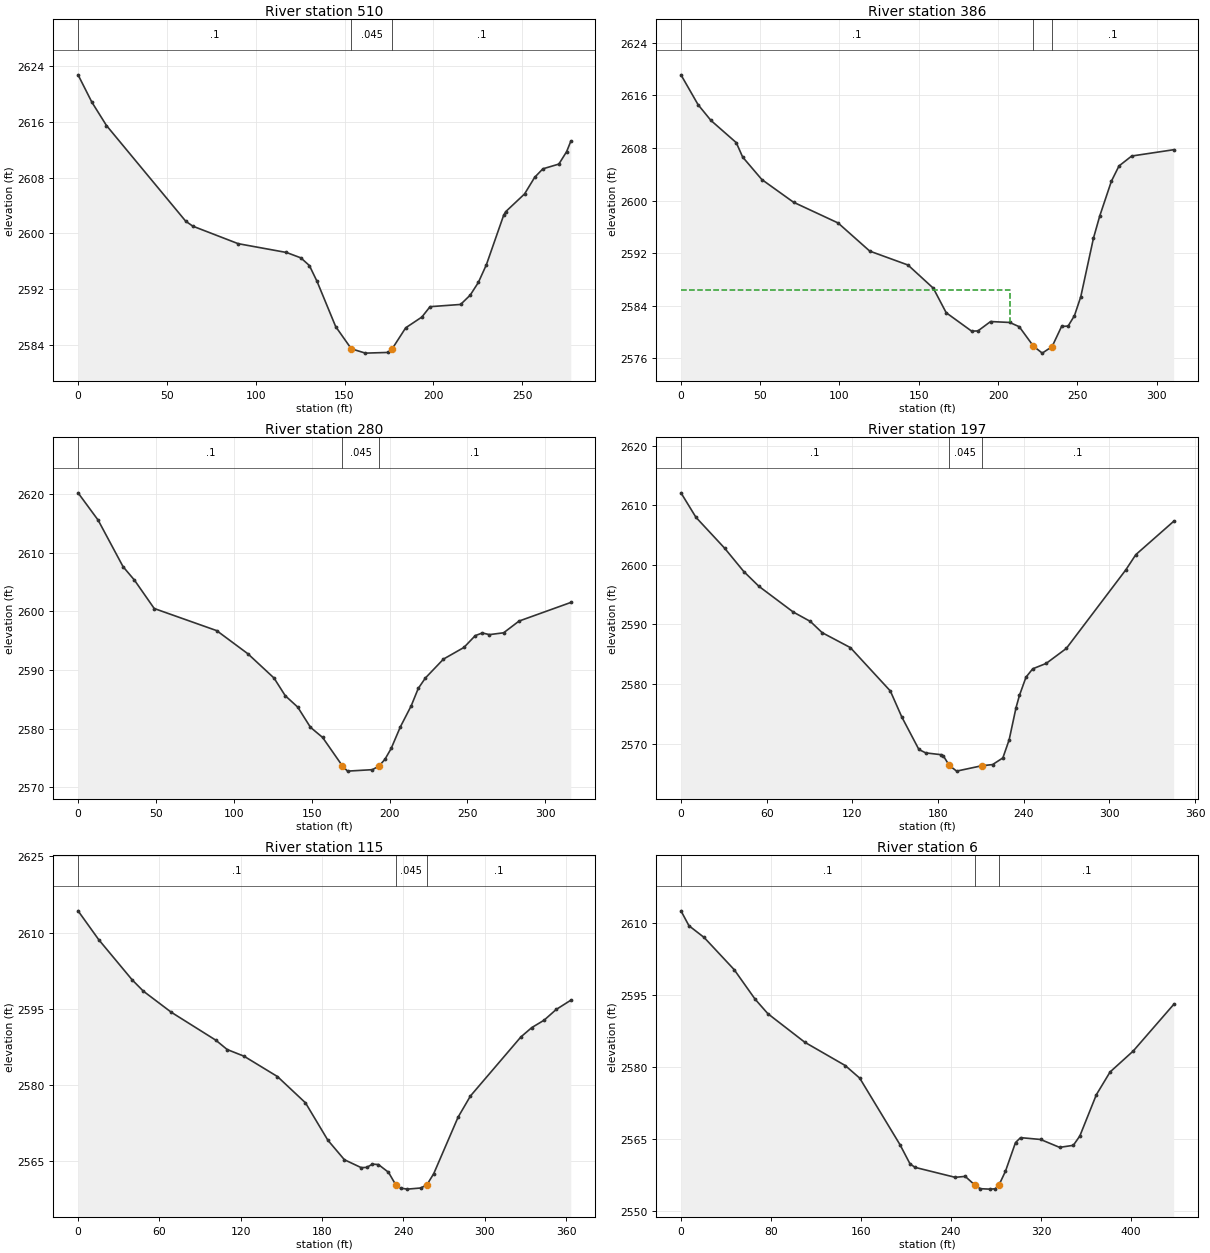
Type RM Length L Ch R = 1 ,510     ,123.9,123.9,123.9
XS GIS Cut Line= 3
2181240.17144375602253.444335659 2181260.0151591602372.506627762
2181398.01917949602446.469566796
#Sta/Elev= 30
       0 2622.68     7.8 2618.76      16 2615.43    60.6 2601.75    64.6 2601.04
    90.1 2598.54   117.3 2597.28   125.4 2596.51   130.2 2595.41   134.5 2593.15
     145 2586.68   153.8 2583.51   161.7 2582.89   174.5 2582.99   176.92583.549
   184.4 2586.51   193.5 2588.05   198.1 2589.53   215.3 2589.85   220.7 2591.18
   225.3    2593   229.8 2595.52   239.5 2602.58   240.7 2603.12   251.3 2605.65
     257 2608.03   261.6 2609.24   270.6 2609.92     275 2611.71   277.3 2613.17
#Mann= 3 ,-1,0
       0      .1       0   153.8    .045       0   176.9      .1       0
Bank Sta=153.8,176.9
XS Rating Curve= 0 ,0
Exp/Cntr(USF)=0,0
Exp/Cntr=0.3,0.1

Type RM Length L Ch R = 1 ,386     ,105.6,105.6,105.6
XS GIS Cut Line= 4
2181196.48162487602258.3601027412181211.43696833602463.749551827
2181228.87266589602493.1337456082181234.62211623602563.593595811
#Sta/Elev= 30
       0  2619.1    10.8 2614.56    18.9 2612.17    34.9 2608.79    38.9 2606.61
      51 2603.19      71 2599.74    99.1 2596.59   119.1 2592.31   143.2  2590.2
   159.2 2586.67   167.3 2582.95   183.3 2580.16   187.3 2580.18   195.3 2581.61
   207.4 2581.47   213.4 2580.82222.35732577.861   227.9 2576.81234.09852577.801
   240.1 2580.87   244.2 2580.92   248.2  2582.5   252.2 2585.38   260.2 2594.28
   264.2 2597.68   271.5 2602.93   276.3 2605.25   284.3 2606.76   310.8 2607.72
#Mann= 3 ,-1,0
       0      .1       0222.3573    .045       0234.0985      .1       0
#XS Ineff= 2 , 0
       0   207.4 2586.47               0
Permanent Ineff=
       F       F
Bank Sta=222.3573,234.0985
XS Rating Curve= 0 ,0
Exp/Cntr(USF)=0,0
Exp/Cntr=0.3,0.1

Type RM Length L Ch R = 1 ,280     ,83.1,83.1,83.1
XS GIS Cut Line= 3
 2181128.3564443602276.247899934  2181122.841948602483.113581013
2181175.55679378602578.874298198
#Sta/Elev= 30
       0  2620.2    12.9 2615.54    28.9 2607.61    36.2 2605.32    48.9 2600.48
      89 2596.71     109 2592.77   125.8 2588.63     133 2585.62     141 2583.68
   149.2 2580.23     157  2578.5  169.74 2573.64     173 2572.76     189 2573.01
  193.29 2573.66     197 2574.77     201 2576.62   206.9  2580.3   213.9 2583.91
   218.4 2586.86     223 2588.64   234.6 2591.86   247.7 2593.84     255 2595.86
   259.5 2596.31   264.1 2596.03   273.2 2596.34   283.1 2598.34   316.3 2601.51
#Mann= 3 ,-1,0
       0      .1       0  169.74    .045       0  193.29      .1       0
Bank Sta=169.74,193.29
XS Rating Curve= 0 ,0
Exp/Cntr(USF)=0,0
Exp/Cntr=0.3,0.1

Type RM Length L Ch R = 1 ,197     ,82.2,82.2,82.2
XS GIS Cut Line= 4
2181032.41414611602310.6606149682181025.83370494602477.704287293
2181085.19373366602512.1967844382181141.90688271602605.427934997
#Sta/Elev= 30
       0 2612.09    10.5 2607.98    30.5 2602.82      44 2598.88    54.6  2596.4
    78.6 2592.09    90.6 2590.51    98.9 2588.62   118.6 2586.12   146.6 2578.84
   154.6 2574.49   166.6 2569.02   171.4 2568.45   182.1 2568.15   183.8 2567.92
187.80952566.374     193 2565.39210.45952566.285   218.2 2566.49   225.4 2567.61
   229.8 2570.65   234.6 2576.02     237  2578.1   241.6 2581.16   246.3 2582.56
   255.7 2583.46   269.8 2585.97   311.5 2599.17   318.5 2601.72     345 2607.31
#Mann= 3 ,-1,0
       0      .1       0187.8095    .045       0210.4595      .1       0
Bank Sta=187.8095,210.4595
XS Rating Curve= 0 ,0
Exp/Cntr(USF)=0,0
Exp/Cntr=0.3,0.1

Type RM Length L Ch R = 1 ,115     ,109,109,109
XS GIS Cut Line= 3
2181024.70850606602306.4372171762180972.27106118602517.465958781
 2181040.4823716602646.641127884
#Sta/Elev= 30
       0 2614.28    15.2 2608.61    39.9 2600.67    48.2 2598.43    68.8 2594.27
   101.7 2588.75     110 2586.92   122.4 2585.61   147.1 2581.59   167.8  2576.4
   184.3 2569.03   196.5 2565.18   208.9 2563.62     213 2563.67   217.2 2564.31
   221.6 2564.23     229 2562.71   234.4 2560.23   237.9 2559.58   242.9 2559.38
   252.7  2559.6   257.3 2560.21   262.4 2562.43   280.4 2573.59   289.5 2577.76
   326.7  2589.4   334.7 2591.24   343.8  2592.7   352.8 2594.83   363.5 2596.64
#Mann= 3 ,-1,0
       0      .1       0   234.4    .045       0   257.3      .1       0
Bank Sta=234.4,257.3
XS Rating Curve= 0 ,0
Exp/Cntr(USF)=0,0
Exp/Cntr=0.3,0.1

Type RM Length L Ch R = 1 ,6       ,,,
XS GIS Cut Line= 3
2181005.52407501602306.8635378662180860.57504037602598.466889902
2180883.59635764 602708.45762795
#Sta/Elev= 30
       0 2612.58     7.1 2609.47    20.6 2607.02    47.3 2600.31    65.9 2594.15
    77.3 2591.11   110.1 2585.16     146 2580.31   158.9 2577.68   194.7  2563.8
   203.6  2559.8   208.1 2559.06   243.8 2556.98   252.7 2557.18  261.16 2555.39
   266.1 2554.61   274.3 2554.52   279.5 2554.59  282.78 2555.41   288.5 2558.27
   297.4 2564.23   301.9 2565.26   319.7 2564.88   336.6 2563.23   348.8 2563.66
   354.6 2565.61   369.3 2574.23   381.5 2578.97     402 2583.32438.0162 2593.05
#Mann= 3 ,-1,0
       0      .1       0  261.16    .045       0  282.78      .1       0
Bank Sta=261.16,282.78
XS Rating Curve= 0 ,0
Exp/Cntr(USF)=0,0
Exp/Cntr=0.3,0.1
LCMann Table=0

Chan Stop Cuts=-1
Use User Specified Reach Order=0
Composite Channel Slope=5